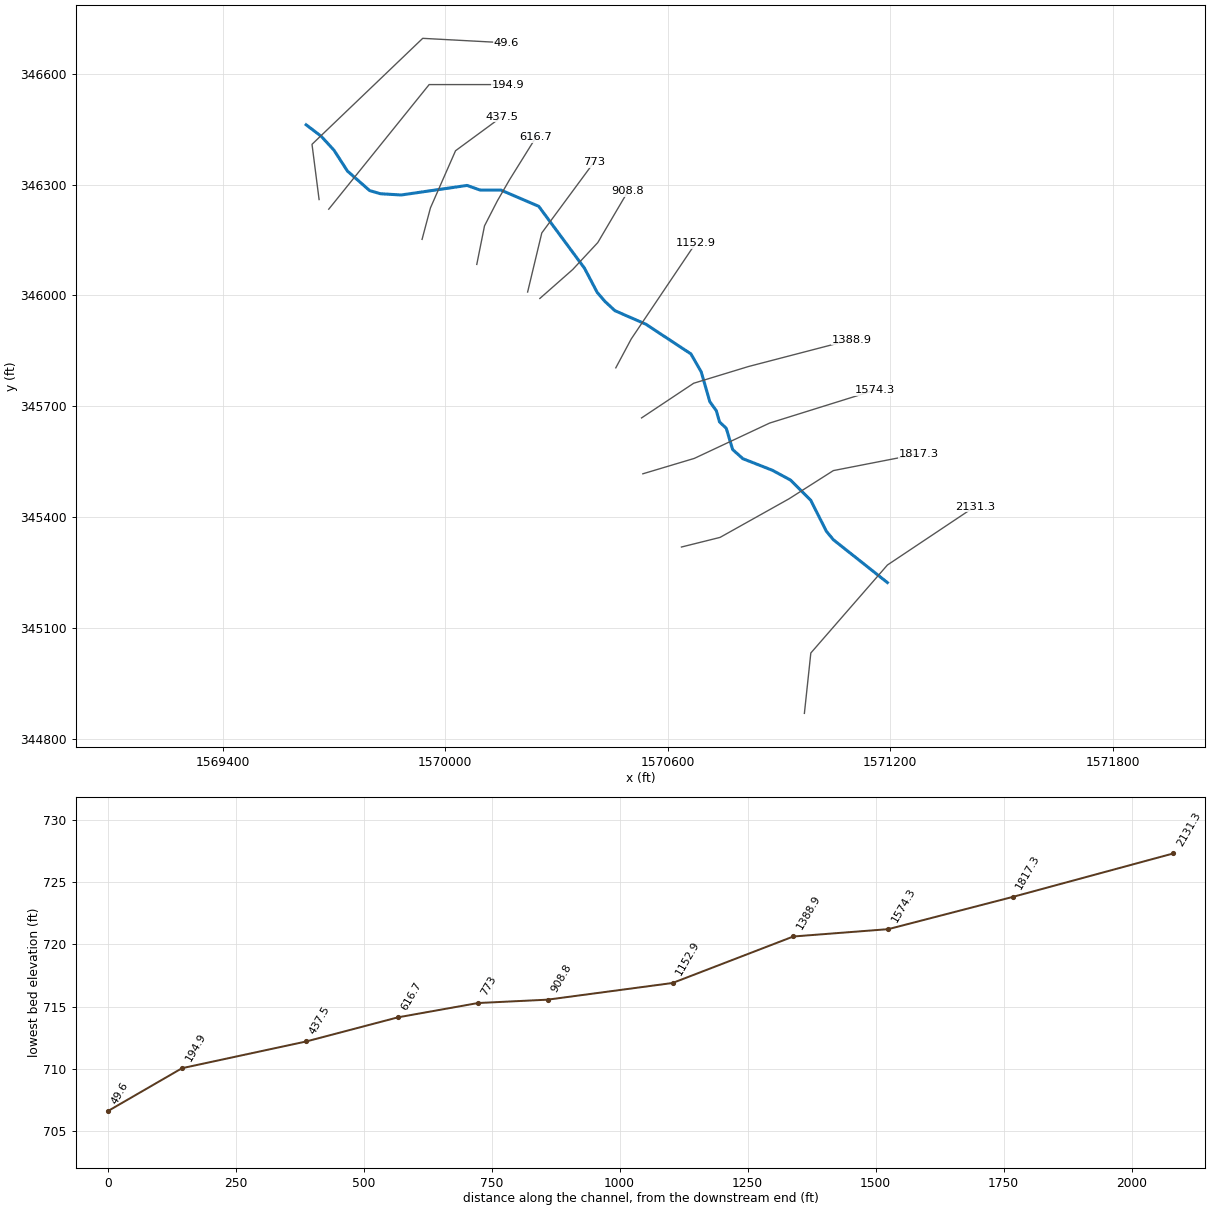
--- FOSTERRN.prj (project) ---

Proj Title=FOSTERRN
Current Plan=p01
Default Exp/Contr=0,0
English Units
Geom File=g01
Flow File=f01
Plan File=p01
BEGIN DESCRIPTION:
END DESCRIPTION:
DSS Export Rating Curves= 0
DSS Export Rating Curve Sorted= 0
DSS Export Volume Flow Curves= 0
DXF OffsetX= 0
DXF OffsetY= 0
DXF ScaleX= 0
DXF ScaleY= 0

--- FOSTERRN.p01 (plan) ---

Plan Title=Floodplain
Program Version=4.00
Geom File=g01
Flow File=f01
K Sum by GR=0
Std Step Tol=0.01
Critical Tol=0.01
Num of Std Step Trials=20
Max Error Tol=0.3
Flow Tol Ratio=0.001
Split Flow NTrial=30
Split Flow Tol=0.02
Split Flow Ratio=0.02
Log Output Level=0
Friction Slope Method=1
Unsteady Friction Slope Method=2
Unsteady Bridges Friction Slope Method=1
Global Log Level=0
CheckData=False
Run HTab=0
Run UNet=0
Run PostProcess=0
UNET Theta=0
UNET Theta Warmup=0
UNET ZTol=0
UNET ZSATol=0
UNET MxIter=0
UNET MaxInSteps=0
UNET DtIC=0
UNET DtMin=0
UNET MaxCRTS=0
UNET WFStab=0
UNET SFStab=0
UNET WFX=0
UNET SFX=0
UNET DSS MLevel=0
UNET DZMax Abort=0
UNET Convert EG Bridges=0
UNET Use Existing IB Tables=0
UNET Froude Limit=0
UNET Froude Power=0
Write IC File=0
Echo Input=False
Echo Output=False
Write Detailed=0

--- FOSTERRN.f01 (steady flow) ---

Flow Title=NFF Regression Equation
Program Version=4.10
Number of Profiles= 1
Profile Names=P100yr
River Rch & RM=FOSTERRN,Main            ,2131.3
877.5438
River Rch & RM=FOSTERRN,Main            ,1574.3
943.3358
River Rch & RM=FOSTERRN,Main            ,437.5
990.8595
Boundary for River Rch & Prof#=FOSTERRN,Main            , 1
Up Type= 0
Dn Type= 3
Dn Slope=0.02
DSS Import GetInterval= 0
DSS Import GetPeak= 0
DSS Import FillOption= 0

--- FOSTERRN.g01 (geometry) ---

Geom Title=USGS 10m DEM
Program Version=4.10

River Reach=FOSTERRN        ,Main
Reach XY= 30
     1571192.806      345223.997      1571046.94      345339.906
     1571028.152      345362.758     1570986.039      345446.499
     1570931.352      345501.186     1570882.307      345527.662
      1570802.88      345558.912     1570775.381      345583.609
     1570758.175      345640.943     1570739.945      345658.304
     1570731.265      345688.686     1570713.888      345712.784
     1570690.548       345793.64     1570662.751      345842.155
     1570540.997      345922.545       1570457.9      345958.891
     1570431.013      345983.905     1570410.013      346008.332
     1570375.796      346073.669     1570252.306      346241.069
     1570150.098      346285.018     1570094.112      346285.041
     1570058.945      346297.478     1569881.312      346271.689
      1569825.12      346275.072     1569796.182      346283.608
     1569736.279      346336.415     1569700.024      346392.774
     1569665.385      346430.561     1569624.915      346461.362

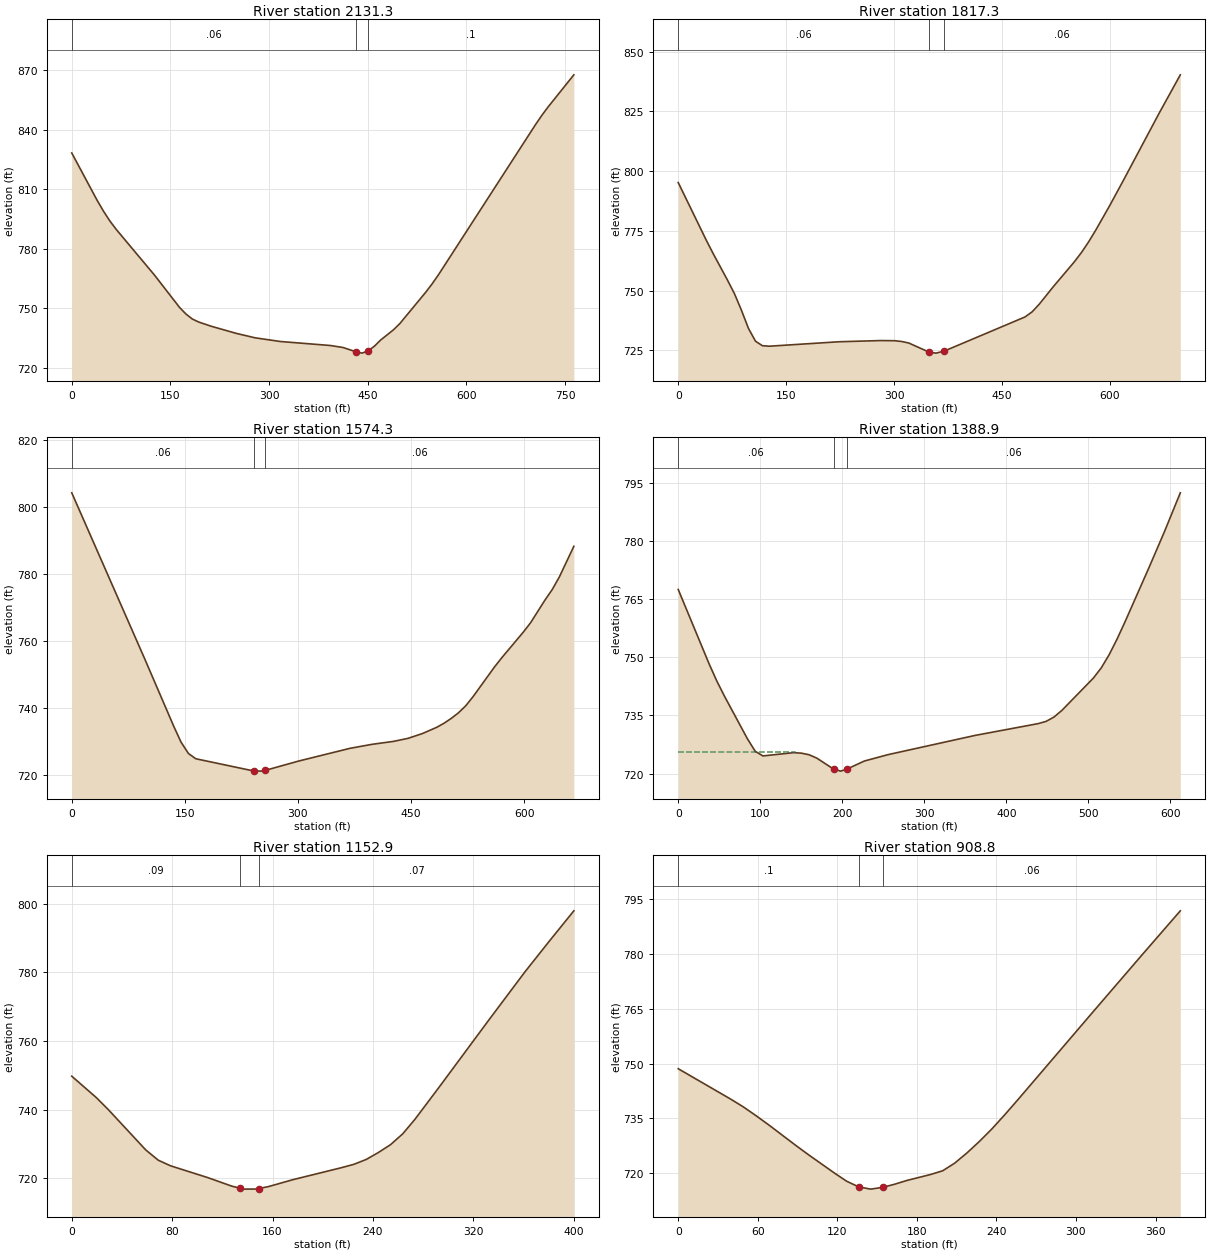
Type RM Length L Ch R = 1 ,2131.3  ,320.9,314,307.7
XS GIS Cut Line= 4
     1570968.903      344870.447     1570986.265      345033.642
     1571192.862      345271.489     1571428.973      345429.475
#Sta/Elev= 30
       0  828.24    38.6  804.34    48.3  798.86    57.9  793.96    67.6   789.7
   125.5  766.76   164.1  750.26   173.7  746.99   183.2  744.53   192.8  743.01
   211.8  740.88     250  737.28   278.7  735.03   316.9  733.18   393.2  731.15
   412.3  730.15   431.4  728.06     441  727.31   449.9  728.28   460.1  730.83
   469.6  733.93     489  739.06   498.8  742.26   537.9  757.95   547.7   762.2
   557.5  766.86   704.5  842.32   714.3   847.1   724.1  851.47   763.2  867.65
#Mann= 3 , 0 , 0
       0     .06       0   431.4    .045       0   449.9      .1       0
Bank Sta=431.4,449.9
XS Rating Curve= 0 ,0
Exp/Cntr=0.3,0.1

Type RM Length L Ch R = 1 ,1817.3  ,245.1,243,239.3
XS GIS Cut Line= 5
     1570637.306        345320.1     1570741.473      345346.142
     1570927.237      345450.308     1571047.028      345526.697
     1571277.931      345571.836
#Sta/Elev= 30
       0  795.19      39  771.05    48.8  765.32    68.3  754.45    78.1  748.71
    87.8  741.78    97.6  734.15   107.4   728.8     117  726.91   126.7  726.71
   223.5  728.57   281.6  729.07     301     729   310.7  728.67   320.4  728.04
   348.8   724.2   358.2  723.81   369.5  724.65     482  738.96   491.8  741.09
   501.6  744.26   521.2  751.61   550.6  762.08   560.4  765.95   570.3  770.37
   580.1  775.23   599.7  785.61   619.3   796.5   668.3  824.23   697.7  840.28
#Mann= 3 , 0 , 0
       0     .06       0   348.8    .045       0   369.5     .06       0
Bank Sta=348.8,369.5
XS Rating Curve= 0 ,0
Exp/Cntr=0.3,0.1

Type RM Length L Ch R = 1 ,1574.3  ,188.1,185.4,181.7
XS GIS Cut Line= 4
      1570533.14      345518.017     1570672.028      345559.683
     1570875.153      345655.169      1571158.14      345743.711
#Sta/Elev= 30
       0  804.13    96.7   754.7   135.3  734.57     145  729.84   154.8  726.47
   164.5  724.91   241.3  721.27   242.6  721.22   252.4  721.25   256.3  721.42
   301.1  724.23   369.4  728.03   398.2   729.2   426.8  730.08     446  730.98
   465.1  732.41   484.2  734.28   493.8  735.49   503.4  736.93   512.9  738.58
   522.5  740.66   532.1  743.34   560.8  752.27   570.3  754.97     599  762.64
   608.6  765.42   627.7  772.18   637.3   775.3   646.8  779.08     666   788.2
#Mann= 3 , 0 , 0
       0     .06       0   241.3    .045       0   256.3     .06       0
Bank Sta=241.3,256.3
XS Rating Curve= 0 ,0
Exp/Cntr=0.3,0.1

Type RM Length L Ch R = 1 ,1388.9  ,220.5,236,251.4
XS GIS Cut Line= 4
     1570529.667      345669.058     1570670.292      345762.808
     1570817.862      345807.947     1571097.376      345880.864
#Sta/Elev= 30
       0  767.46    37.6  748.31      47  743.88    56.3  739.98    84.5  728.92
    93.9  725.74   103.3  724.55   140.8  725.39   150.2  725.26   159.6  724.85
     169  723.98   188.3  721.31   190.4  721.16   197.9  720.63   205.4  721.12
   226.9  723.23   255.8  724.88   361.8  729.83   438.9  732.88   448.5  733.45
   458.1  734.56   467.8  736.29   506.3  744.64   515.9  747.27   525.5  750.67
   535.2  754.72   544.8  759.13   573.7  772.95   592.9  782.39   612.2  792.38
#Mann= 3 , 0 , 0
       0     .06       0   190.4    .045       0   205.4     .06       0
#XS Ineff= 2 , 0
          141.98  725.61
Permanent Ineff=
       F       F
Bank Sta=190.4,205.4
XS Rating Curve= 0 ,0
Exp/Cntr=0.3,0.1

Type RM Length L Ch R = 1 ,1152.9  ,247.6,244.1,240.3
XS GIS Cut Line= 3
     1570460.223      345804.475      1570501.89        345882.6
     1570675.501      346141.281
#Sta/Elev= 26
       0  749.77    19.7   743.5    29.5   739.9      59  728.29    68.9  725.32
    78.7  723.68     108  720.29   127.5  717.76   134.1  717.17   137.2  716.89
     147  716.92   149.1  717.07   156.7  717.62   176.2  719.64   215.1  723.15
   224.8  724.11   234.6  725.52   244.3  727.54     254  729.83   263.8  733.01
   273.5  737.23     293   746.7   331.9   765.9   361.1  780.13   380.6  789.11
   400.1  797.92
#Mann= 3 , 0 , 0
       0     .09       0   134.1    .045       0   149.1     .07       0
Bank Sta=134.1,149.1
XS Rating Curve= 0 ,0
Exp/Cntr=0.3,0.1

Type RM Length L Ch R = 1 ,908.8   ,132.4,135.8,138
XS GIS Cut Line= 4
     1570255.362      345991.975     1570343.903        346070.1
     1570411.612      346143.017     1570493.209      346281.906
#Sta/Elev= 25
       0  748.57    39.4  740.27    49.2  738.08      59  735.61    68.9  732.99
    88.6  727.56    98.4  724.94   118.1  719.89   127.1   717.7   136.2  716.16
   145.2  715.55   154.3  716.04   163.3   716.9   172.4  717.92   190.4  719.57
   199.5  720.59   208.5  722.67   217.6  725.42   227.1  728.61   236.5  732.03
     246  735.83   255.5  739.78   312.3  763.92   350.2  779.94   378.7  791.87
#Mann= 3 , 0 , 0
       0      .1       0   136.2    .045       0   154.3     .06       0
Bank Sta=136.2,154.3
XS Rating Curve= 0 ,0
Exp/Cntr=0.3,0.1

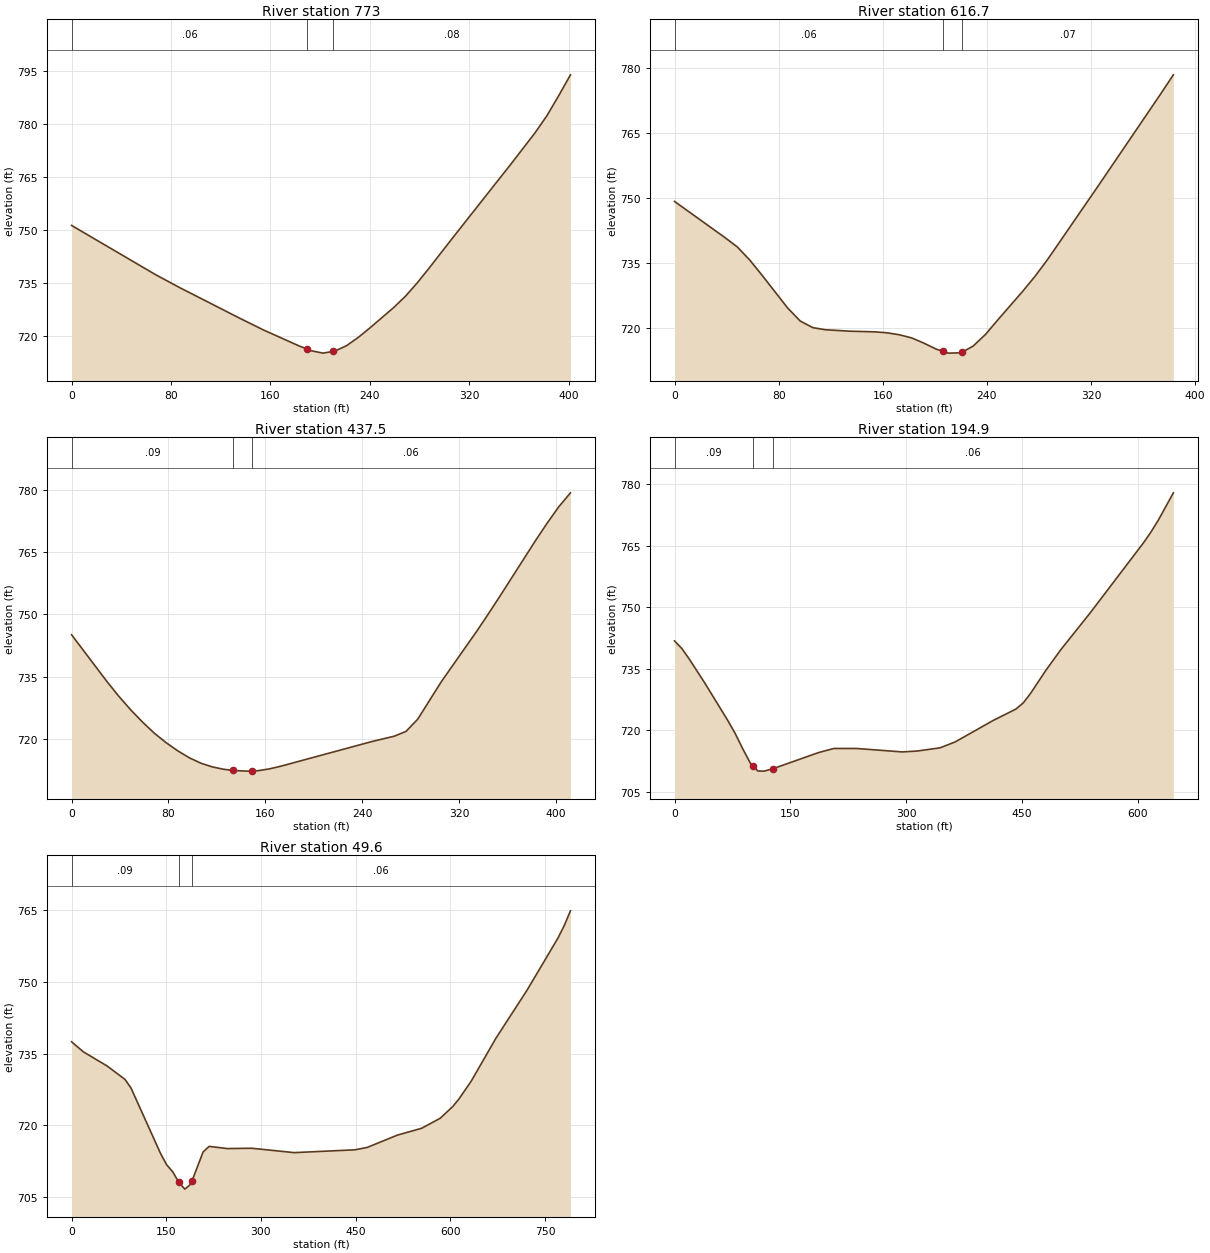
Type RM Length L Ch R = 1 ,773     ,154.4,156.3,159.2
XS GIS Cut Line= 3
     1570222.376      346009.336      1570260.57      346169.058
     1570401.195      346360.031
#Sta/Elev= 24
       0  751.41    67.6  737.48    86.9  733.83   135.2  725.17   154.6   721.8
   183.2  717.29  189.55  716.45   192.7  715.97   202.2  715.28   210.7  715.78
   211.7  715.84   221.1  717.36   230.6  719.71   240.1  722.43   259.1  728.16
   268.6  731.36   278.1  735.15   287.6   739.3   306.5  747.84     354     769
   372.9  777.61   382.4  782.43   391.9  788.09   401.4  794.03
#Mann= 3 , 0 , 0
       0     .06       0  189.55    .045       0   210.7     .08       0
Bank Sta=189.55,210.7
XS Rating Curve= 0 ,0
Exp/Cntr=0.3,0.1

Type RM Length L Ch R = 1 ,616.7   ,177.6,179.2,177.3
XS GIS Cut Line= 5
     1570085.223      346083.989     1570106.056      346188.156
     1570140.778      346255.864     1570173.765      346313.156
     1570244.945      346427.739
#Sta/Elev= 29
       0   749.2    38.6  740.87    48.3  738.66    57.9  735.62    67.6  732.01
    86.9  724.57    96.6  721.55   106.2  720.03   115.7  719.54   134.8   719.2
   153.8  719.05   163.3  718.83   172.8  718.37   182.3  717.64   191.8  716.41
   201.2  715.04     206  714.58   210.6  714.13   220.1   714.2     221  714.35
   229.5  715.77     239  718.47   248.4  721.81   267.7  728.48   277.3     732
     287  735.92   325.5  752.76   373.7  774.11   383.3  778.46
#Mann= 3 , 0 , 0
       0     .06       0     206    .045       0     221     .07       0
Bank Sta=206,221
XS Rating Curve= 0 ,0
Exp/Cntr=0.3,0.1

Type RM Length L Ch R = 1 ,437.5   ,246.2,242.6,239.8
XS GIS Cut Line= 4
     1569937.653      346151.697     1569960.223      346236.767
     1570027.931      346391.281     1570152.931      346483.294
#Sta/Elev= 30
       0   745.1    29.3  733.77    39.1  730.21    48.9  726.95    58.7  723.99
    68.4  721.32    78.2  719.02      88  717.02    97.4  715.38   106.8   714.1
   116.1  713.22   125.5  712.64   133.6  712.35   144.2  712.19   148.6  712.23
   153.6  712.28     163  712.71   172.4  713.35   247.3  719.28   266.4  720.62
   276.1  721.77   285.8  724.72   305.2  733.74   334.3  745.86     344  750.08
   353.7  754.42   382.8  767.71   392.5  771.96   402.2  775.96   411.9  779.35
#Mann= 3 , 0 , 0
       0     .09       0   133.6    .045       0   148.6     .06       0
Bank Sta=133.6,148.6
XS Rating Curve= 0 ,0
Exp/Cntr=0.3,0.1

Type RM Length L Ch R = 1 ,194.9   ,147.9,145.3,142
XS GIS Cut Line= 3
     1569685.917      346233.294     1569956.751        346570.1
     1570170.292        346570.1
#Sta/Elev= 30
       0  741.77     9.8  739.84    19.6   737.2    39.3  731.48    68.8  722.43
    78.6  719.19    88.4  715.45    98.2  711.97   101.1   711.4     108  710.06
   116.1  710.04   127.7  710.65   186.6  714.57   206.3  715.56   235.7  715.56
   294.7  714.72   314.3  714.94   343.8  715.72   363.4  717.17   412.6   722.4
   441.9  725.16   451.6  726.69   461.3   729.1   480.7  734.61   500.1  739.65
     539  748.83   606.9  765.64   616.6  768.27   626.3  771.21   645.7  777.85
#Mann= 3 , 0 , 0
       0     .09       0   101.1    .045       0   127.7     .06       0
Bank Sta=101.1,127.7
XS Rating Curve= 0 ,0
Exp/Cntr=0.3,0.1

Type RM Length L Ch R = 1 ,49.6    ,46.1,49.6,53.2
XS GIS Cut Line= 4
     1569659.876      346259.336     1569640.778      346408.642
      1569939.39        346695.1     1570165.084      346682.947
#Sta/Elev= 30
       0  737.46    18.8  735.34    56.4  732.38    84.7  729.56    94.1  727.77
   141.1     714   150.5   711.7   160.2  710.21   169.8  708.02   179.4  706.58
     189  707.64   190.8  708.31   208.3  714.37   217.9  715.54   246.8  715.08
   285.2  715.15   352.6  714.23   448.8  714.82   468.1  715.31   516.2   717.9
   554.7  719.34     584  721.44   603.6  723.86   613.4  725.42   633.1  729.22
   672.4  738.24   721.6  748.29   770.7  759.24   780.5  761.83   790.3  764.91
#Mann= 3 , 0 , 0
       0     .09       0   169.8    .045       0   190.8     .06       0
Bank Sta=169.8,190.8
XS Rating Curve= 0 ,0
Exp/Cntr=0.3,0.1

Chan Stop Cuts=-1
Use User Specified Reach Order=0
Composite Channel Slope=5